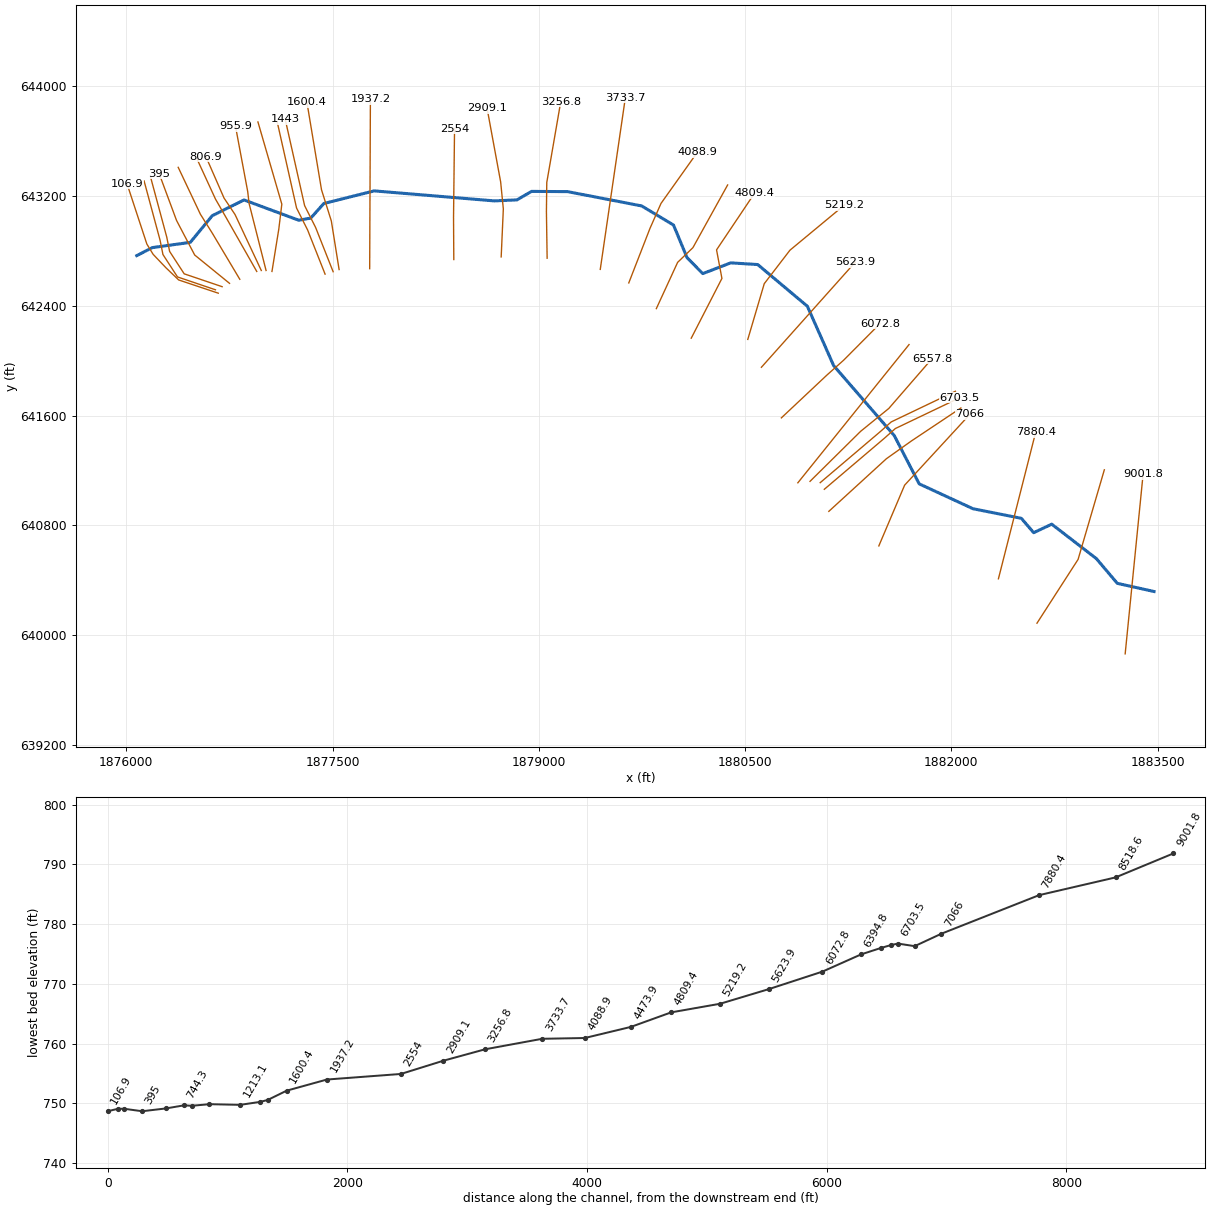
--- VandaleFrk.prj (project) ---

Proj Title=VandaleFrk
Current Plan=p01
Default Exp/Contr=0,0
English Units
Geom File=g01
Flow File=f01
Plan File=p01
BEGIN DESCRIPTION:
AMEC Environment & Infrastructure, 2013
Projection: NAD 1983 State Plane West Virginia South FIPS 4702 (US Feet)
Vertical Datum: NAVD 1988
END DESCRIPTION:
DSS Export Rating Curves= 0
DSS Export Rating Curve Sorted= 0
DSS Export Volume Flow Curves= 0
DXF OffsetX= 0
DXF OffsetY= 0
DXF ScaleX= 0
DXF ScaleY= 0

--- VandaleFrk.p01 (plan) ---

Plan Title=Floodplain
Program Version=4.00
Geom File=g01
Flow File=f01
K Sum by GR=0
Std Step Tol=0.01
Critical Tol=0.01
Num of Std Step Trials=20
Max Error Tol=0.3
Flow Tol Ratio=0.001
Split Flow NTrial=30
Split Flow Tol=0.02
Split Flow Ratio=0.02
Log Output Level=0
Friction Slope Method=1
Unsteady Friction Slope Method=2
Unsteady Bridges Friction Slope Method=1
Global Log Level=0
CheckData=False
Run HTab=0
Run UNet=0
Run PostProcess=0
UNET Theta=0
UNET Theta Warmup=0
UNET ZTol=0
UNET ZSATol=0
UNET MxIter=0
UNET MaxInSteps=0
UNET DtIC=0
UNET DtMin=0
UNET MaxCRTS=0
UNET WFStab=0
UNET SFStab=0
UNET WFX=0
UNET SFX=0
UNET DSS MLevel=0
UNET DZMax Abort=0
UNET Convert EG Bridges=0
UNET Use Existing IB Tables=0
UNET Froude Limit=0
UNET Froude Power=0
Write IC File=0
Echo Input=False
Echo Output=False
Write Detailed=0

--- VandaleFrk.f01 (steady flow) ---

Flow Title=NFF Regression Equation
Program Version=4.10
Number of Profiles= 1
Profile Names=P100yr
River Rch & RM=VandaleFrk,Main            ,9001.8
888.6882
River Rch & RM=VandaleFrk,Main            ,7066
941.8351
River Rch & RM=VandaleFrk,Main            ,5219.2
 1044.03
River Rch & RM=VandaleFrk,Main            ,4809.4
1160.094
River Rch & RM=VandaleFrk,Main            ,3256.8
1194.079
River Rch & RM=VandaleFrk,Main            ,2909.1
1678.975
River Rch & RM=VandaleFrk,Main            ,594.2
1744.411
River Rch & RM=VandaleFrk,Main            ,245.6
1746.572
Boundary for River Rch & Prof#=VandaleFrk,Main            , 1
Up Type= 0
Dn Type= 3
Dn Slope=0.00492
DSS Import GetInterval= 0
DSS Import GetPeak= 0
DSS Import FillOption= 0

--- VandaleFrk.g01 (geometry) ---

Geom Title=USGS 3m DEM
Program Version=4.10

River Reach=VandaleFrk      ,Main
Reach XY= 30
     1883474.993       640318.83     1883207.769      640378.312
     1883054.927      640558.928     1882730.643      640809.637
     1882599.416      640747.528     1882509.576      640852.416
     1882158.749      640921.872     1881766.727      641103.527
       1881585.6       641455.03     1881144.444      641965.616
     1880953.383      642398.058     1880592.126      642701.974
     1880395.873      642714.123     1880192.677      642635.961
     1880078.002       642752.78     1879979.912      642989.759
     1879748.047      643129.179      1879209.65       643233.36
     1878947.401      643235.086     1878841.146      643173.126
     1878676.379      643165.889     1877802.791      643238.794
     1877436.656      643146.888     1877341.624      643040.509
        1877254.      643024.915     1876856.265      643172.755
     1876625.282      643058.119      1876465.51      642863.597
     1876189.369      642825.376     1876076.059      642767.024

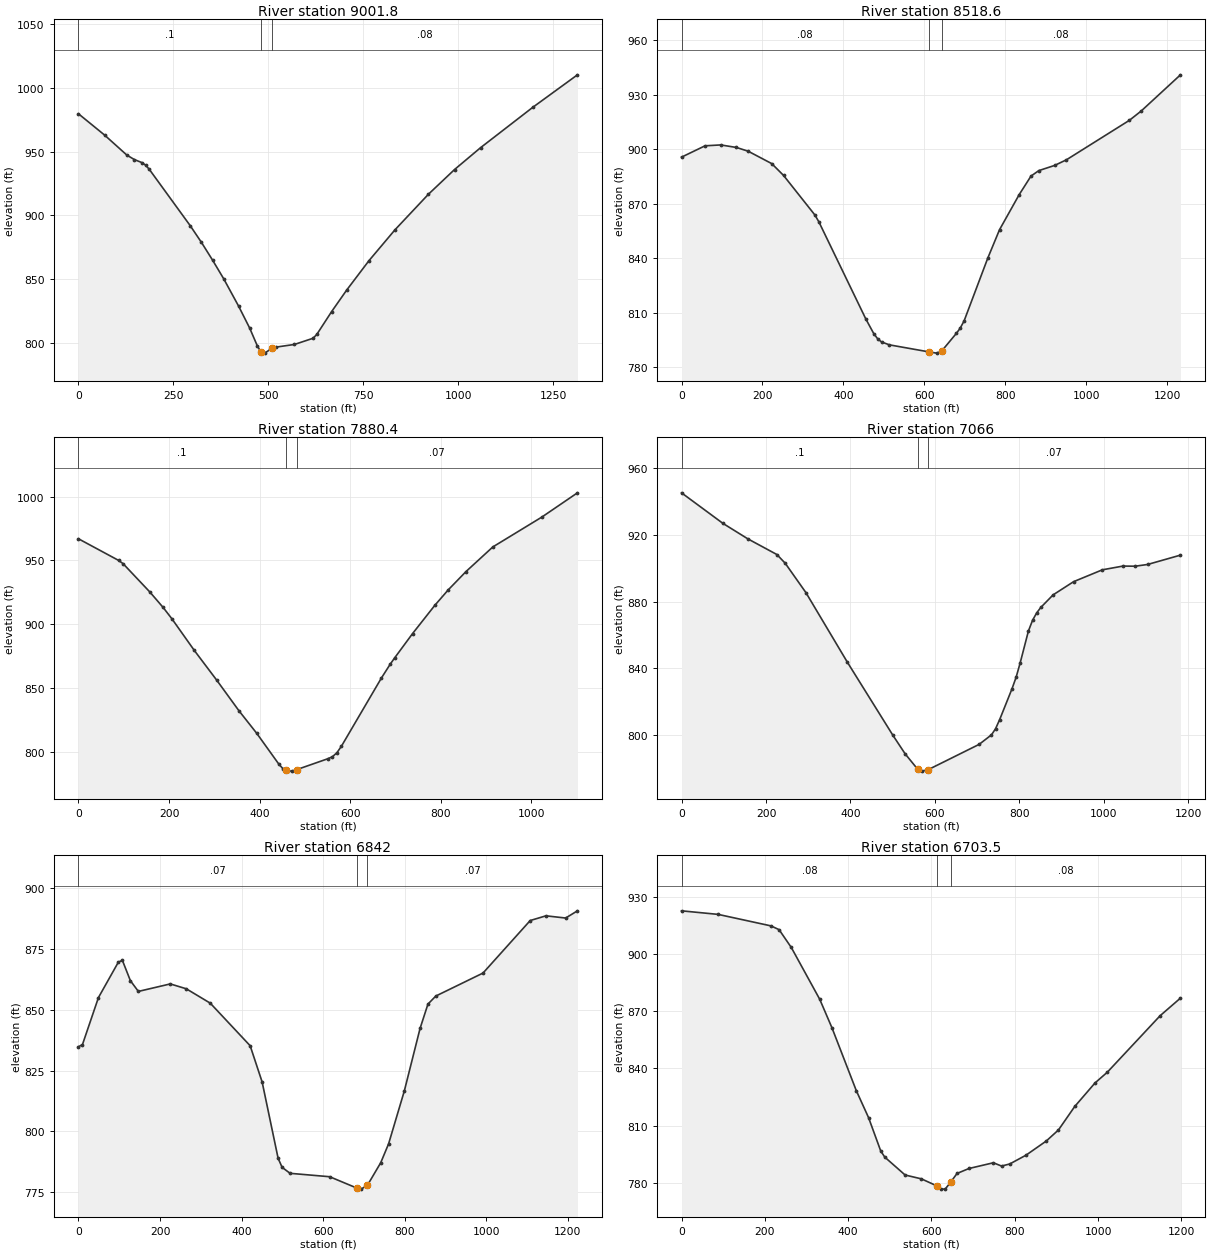
Type RM Length L Ch R = 1 ,9001.8  ,488.9,483.2,479.8
XS GIS Cut Line= 2
     1883264.874      639864.593     1883395.082      641171.885
#Sta/Elev= 30
       0  979.83    68.6  963.16   127.4  947.39   147.1   943.9   166.7  941.54
   176.5  939.56   186.3  936.28   294.1     892   323.5  878.96     353  864.92
   382.4  850.23   421.6  828.77     451  811.37   470.6  797.75   480.4   792.7
   490.2  791.85   509.2  795.57   519.6  796.55   568.6  798.66   617.7  803.53
   627.5  806.54   666.7  824.54   705.9  841.26   764.7  864.42   833.4  888.73
   921.6   916.7   990.2  936.06  1058.8  953.24  1196.1   984.9  1313.8 1010.45
#Mann= 3 , 0 , 0
       0      .1       0   480.4    .045       0   509.2     .08       0
Bank Sta=480.4,509.2
XS Rating Curve= 0 ,0
Exp/Cntr=0.3,0.1

Type RM Length L Ch R = 1 ,8518.6  ,639.1,638.2,634.2
XS GIS Cut Line= 3
     1882623.485      640088.027     1882922.421       640552.87
     1883113.394      641206.082
#Sta/Elev= 30
       0  895.68    58.2  901.92      97   902.4   135.7  901.01   164.8  898.94
     223  892.12   252.1  885.64   329.7  863.83   339.4  860.11   455.7  806.55
   475.1  798.59   484.8  795.71   494.5  793.96   513.9  792.38     611  788.53
   630.4  787.83   642.8  788.91   679.1  798.64   688.8  801.57   698.5   805.6
   756.8  840.03     786  855.75   834.6  875.06   863.8  885.27   883.2  888.28
   922.1  891.12   951.3  894.21  1106.8  915.92    1136  921.04  1233.2  940.98
#Mann= 3 , 0 , 0
       0     .08       0     611    .045       0   642.8     .08       0
Bank Sta=611,642.8
XS Rating Curve= 0 ,0
Exp/Cntr=0.3,0.1

Type RM Length L Ch R = 1 ,7880.4  ,826.7,814.5,802.3
XS GIS Cut Line= 2
     1882342.999      640411.468     1882613.832      641479.177
#Sta/Elev= 30
       0   966.9    88.5  949.98    98.4  947.44   157.4  925.27   186.9  913.09
   206.5  904.09   255.7  879.43   304.9  856.26   354.1  832.23   393.4  814.54
   442.6  790.19   452.4  786.35  458.04  785.53   462.2  784.86   472.1  785.02
   482.1  786.08   550.8  794.61   560.6  796.16   570.4  799.23   580.3  804.28
   668.8  857.86   688.4  868.77   698.3  873.75   737.6  892.67   786.8  914.83
   816.3   926.9   855.6  941.27   914.7  960.52  1022.8  983.89  1101.5 1002.92
#Mann= 3 , 0 , 0
       0      .1       0  458.04    .045       0   482.1     .07       0
Bank Sta=458.04,482.1
XS Rating Curve= 0 ,0
Exp/Cntr=0.3,0.1

Type RM Length L Ch R = 1 ,7066    ,229.3,224,218.6
XS GIS Cut Line= 3
     1881473.207      640651.052     1881660.707       641093.76
     1882134.665      641609.385
#Sta/Elev= 30
       0  945.37    98.1  927.03     157  917.76   225.7  908.36   245.3  903.18
   294.4  885.54   392.5  843.79   500.2  799.98   529.4  788.77   559.5   779.4
   568.3  778.41  583.46  779.23   704.5  794.46   733.7  800.17   743.4  803.85
   753.1  809.32   782.3   827.8     792  834.68   801.8  843.48   821.2   862.5
     831  868.91   840.7  873.31   850.4  876.59   879.6  884.15   928.2  892.08
   996.3  899.19    1045  901.43  1074.1  901.35  1103.3  902.39  1181.1  907.99
#Mann= 3 , 0 , 0
       0      .1       0   559.5    .045       0  583.46     .07       0
Bank Sta=559.5,583.46
XS Rating Curve= 0 ,0
Exp/Cntr=0.3,0.1

Type RM Length L Ch R = 1 ,6842    ,135.8,138.5,141.1
XS GIS Cut Line= 4
     1881109.487      640903.022     1881528.324      641286.703
      1881708.88      641415.175     1882069.991      641656.494
#Sta/Elev= 30
       0  834.77     9.8   835.7      49  854.99    97.9  869.55   107.7  870.25
   127.3  861.91   146.9   857.5   225.2  860.58   264.4  858.58   323.2  852.68
   421.1  835.19   450.5   820.3   489.7  788.96   499.5  785.26     519  782.81
   616.2  781.41   683.6   776.7   693.3  776.32   708.8  777.91   741.4  787.17
   760.7  794.93   799.3  816.65   837.9  842.32   857.2  852.29   876.5   855.6
   992.3  865.04  1108.1  886.61  1146.7  888.54    1195  887.63  1223.9  890.59
#Mann= 3 , 0 , 0
       0     .07       0   683.6    .045       0   708.8     .07       0
Bank Sta=683.6,708.8
XS Rating Curve= 0 ,0
Exp/Cntr=0.3,0.1

Type RM Length L Ch R = 1 ,6703.5  ,56.1,56.1,56.1
XS GIS Cut Line= 4
     1881076.718      641063.938     1881515.086      641437.202
     1881593.211      641506.646     1882059.791      641730.171
#Sta/Elev= 30
       0  922.54    87.8  920.68   214.7  914.65   234.2  912.67   263.5  903.34
   331.8  876.18   361.1  861.27   419.6   828.3   448.9  814.24   478.2  796.71
   487.9  793.51   536.7  784.14   575.8  782.13   613.8  778.35   623.3  776.78
   632.8  776.75   646.6  780.57   661.3  784.96     690  787.56   748.6  790.56
   768.1  788.84   787.7  789.92   826.7  794.51   875.5  801.95   904.8  807.76
   943.8  820.04   992.6  832.39  1021.9  837.97  1148.8   867.6  1197.6  876.82
#Mann= 3 , 0 , 0
       0     .08       0   613.8    .045       0   646.6     .08       0
Bank Sta=613.8,646.6
XS Rating Curve= 0 ,0
Exp/Cntr=0.3,0.1

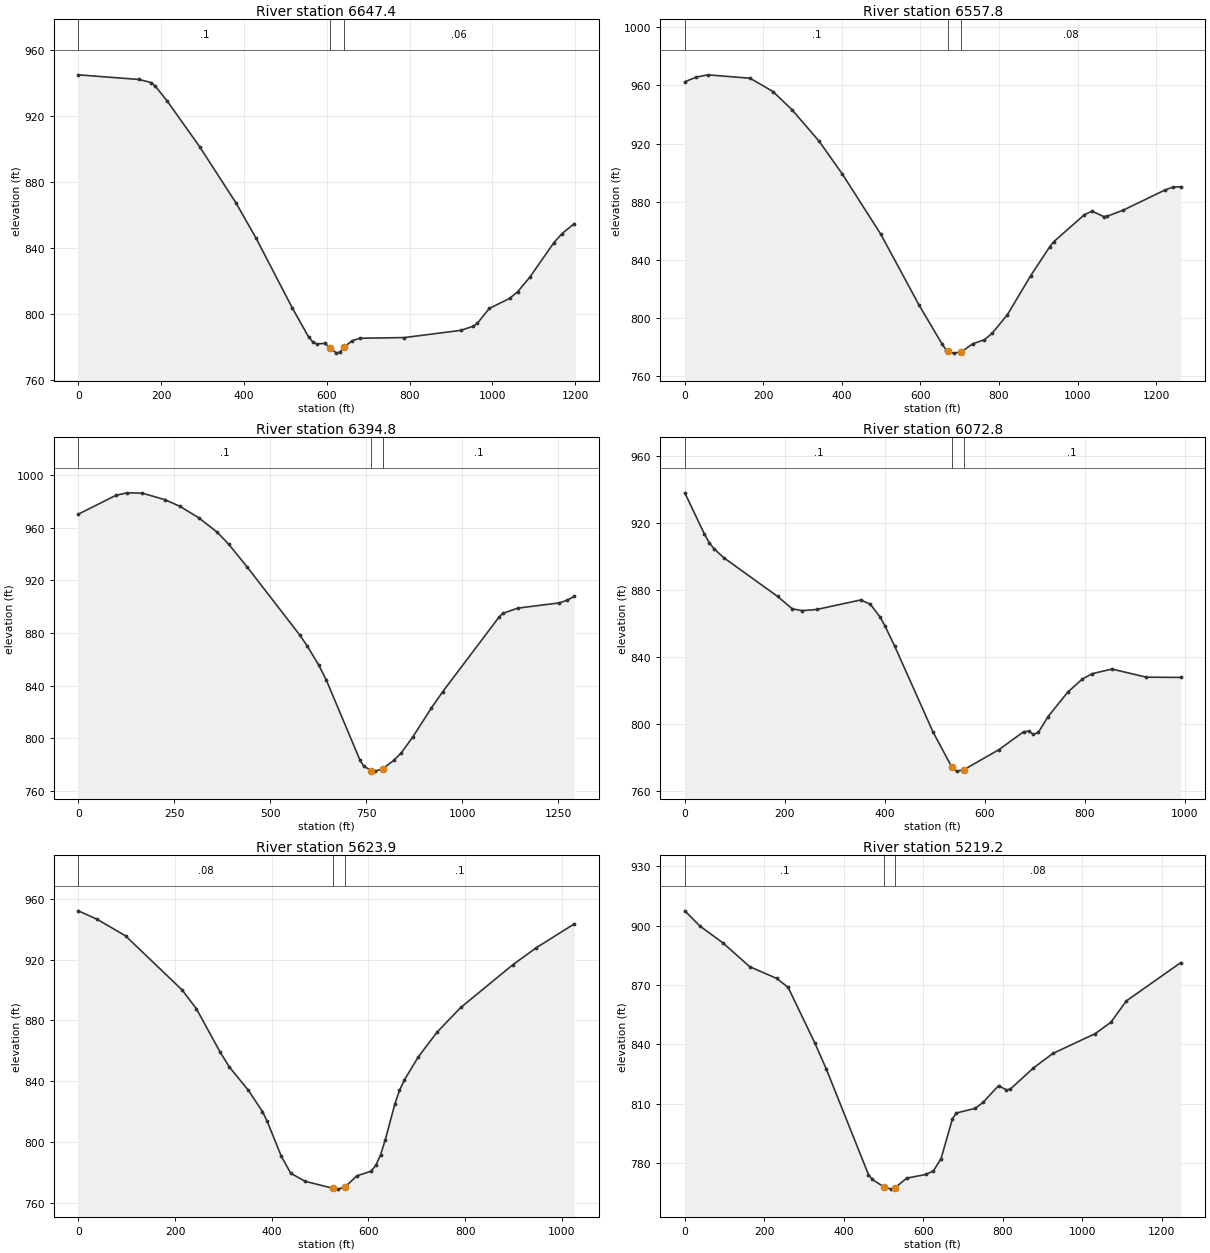
Type RM Length L Ch R = 1 ,6647.4  ,90.7,89.6,88.5
XS GIS Cut Line= 4
      1881046.77      641112.115     1881485.138      641485.379
     1881563.263      641554.823     1882029.843      641778.348
#Sta/Elev= 30
       0  945.07   146.4  942.26   175.6  940.41   185.4  938.37   214.7  929.17
   292.8  901.62   380.6  867.57   429.4  846.11   517.2  803.71   556.2  786.29
     566  783.41   575.8  782.13   594.8  782.42  608.73  779.74   623.3  776.52
   632.8  777.39   642.3  780.26   661.3  784.04   680.3  785.53   787.7  785.94
   924.3  790.34   953.6   792.8   963.4  794.48   992.6  803.59  1041.5  809.62
    1061  813.66  1090.3  822.44  1148.8  843.48  1168.4  848.93  1197.6  854.92
#Mann= 3 , 0 , 0
       0      .1       0  608.73    .045       0   642.3     .06       0
Bank Sta=608.73,642.3
XS Rating Curve= 0 ,0
Exp/Cntr=0.3,0.1

Type RM Length L Ch R = 1 ,6557.8  ,157.6,163,168.3
XS GIS Cut Line= 4
     1880972.769      641121.772     1881340.824      641486.356
     1881545.685      641653.022     1881859.921      642015.869
#Sta/Elev= 30
       0  962.55    29.3  965.73    58.6  967.32   166.2  964.97   224.8  955.79
   273.7   943.1   342.1  921.63   400.8  899.24   498.5  857.96   596.3  809.06
     655  782.23   664.8  778.37  670.43  777.19   684.3     776   703.9  776.84
   733.2  782.46   762.6  785.22   782.2  789.56   821.3  802.44   880.1  829.06
   929.1  849.15   938.9  852.52  1017.3  871.18  1036.8   873.6  1066.2  869.89
    1076  870.19  1115.2  874.17    1223  888.23  1242.6   890.1  1262.2  890.38
#Mann= 3 , 0 , 0
       0      .1       0  670.43    .045       0   703.9     .08       0
Bank Sta=670.43,703.9
XS Rating Curve= 0 ,0
Exp/Cntr=0.3,0.1

Type RM Length L Ch R = 1 ,6394.8  ,326.4,322,316.6
XS GIS Cut Line= 2
     1880884.248      641111.277     1881692.918      642118.568
#Sta/Elev= 30
       0  970.32    97.9  984.62   127.2  986.53   166.4   986.3   225.1  981.38
   264.2  976.34   313.2  967.67   362.1  956.53   391.4   947.6   440.4  929.96
   577.4  878.22   596.9  869.83   626.3   855.6   645.9  844.27   733.9  783.21
   743.7  778.68   763.3   775.4   773.1  774.94   792.7  776.67     822  783.17
   841.6  788.91   870.9  800.76   919.9     823   949.2  835.31    1096  892.07
  1105.8  894.88    1145  898.87  1252.6  902.83  1272.2  904.72  1291.7  907.73
#Mann= 3 , 0 , 0
       0      .1       0   763.3    .045       0   792.7      .1       0
Bank Sta=763.3,792.7
XS Rating Curve= 0 ,0
Exp/Cntr=0.3,0.1

Type RM Length L Ch R = 1 ,6072.8  ,445.5,448.9,453.2
XS GIS Cut Line= 4
     1880764.435      641584.446     1881098.637      641899.116
     1881217.994      642005.453     1881480.581       642270.21
#Sta/Elev= 30
       0  938.27    39.1  913.74    48.8  908.53    58.6   904.8    78.1   899.5
   185.6  876.41   214.9  869.01   234.4  867.91   263.7  868.59   351.6  874.28
   371.1  871.78   390.7  864.06   400.4  858.78     420  846.63   496.6  795.39
   534.3  774.35   543.7  772.06  557.89  772.84   628.7  784.95   677.8  795.61
   687.6  795.92   697.4  793.98   707.2   795.2   726.8  804.68   766.1  819.26
   795.5  827.14   815.1  830.26   854.4  833.03   923.1  828.18   991.8  828.02
#Mann= 3 , 0 , 0
       0      .1       0   534.3    .045       0  557.89      .1       0
Bank Sta=534.3,557.89
XS Rating Curve= 0 ,0
Exp/Cntr=0.3,0.1

Type RM Length L Ch R = 1 ,5623.9  ,403.3,404.7,406.3
XS GIS Cut Line= 2
      1880619.04      641953.135     1881301.332       642718.76
#Sta/Elev= 30
       0  951.99    39.1   946.4    97.7  935.54   214.9  899.91   244.2  887.63
     293  859.34   312.5  849.31   351.6  834.13   380.9  820.06   390.7  813.61
     420   790.6   439.5  779.51   468.8  774.29   527.4  769.61   537.2  769.12
   551.9  770.63   576.2  777.85   605.6  780.92   615.3  784.75   625.1  791.65
   634.8  801.54   654.4  824.74   664.2  833.99   673.9  840.56   703.2  856.04
   742.3   872.4   791.1  888.52   898.6  916.54   947.4  927.78  1025.5  943.36
#Mann= 3 , 0 , 0
       0     .08       0   527.4    .045       0   551.9      .1       0
Bank Sta=527.4,551.9
XS Rating Curve= 0 ,0
Exp/Cntr=0.3,0.1

Type RM Length L Ch R = 1 ,5219.2  ,389,409.8,430.6
XS GIS Cut Line= 4
     1880520.082       642156.26     1880639.874       642562.51
     1880826.783      642806.494     1881223.919      643136.356
#Sta/Elev= 30
       0  907.55    38.5  899.78    96.3  891.25   163.6  879.22     231  873.36
   259.9  868.81   327.3  840.58   356.2  827.34     462  774.07   471.6  771.58
   500.4  767.84   519.6  766.68   529.2  767.42     558  772.23     606   774.1
   625.2  775.89   644.4  782.02   673.3   802.3   682.9   805.2   730.9   807.6
   750.4  810.63   789.3  819.06   808.8  816.93   818.6  817.29     877  828.02
   925.7  835.34  1032.9  845.44  1071.8  851.16  1110.8  861.96  1247.2   881.3
#Mann= 3 , 0 , 0
       0      .1       0   500.4    .045       0   529.2     .08       0
Bank Sta=500.4,529.2
XS Rating Curve= 0 ,0
Exp/Cntr=0.3,0.1

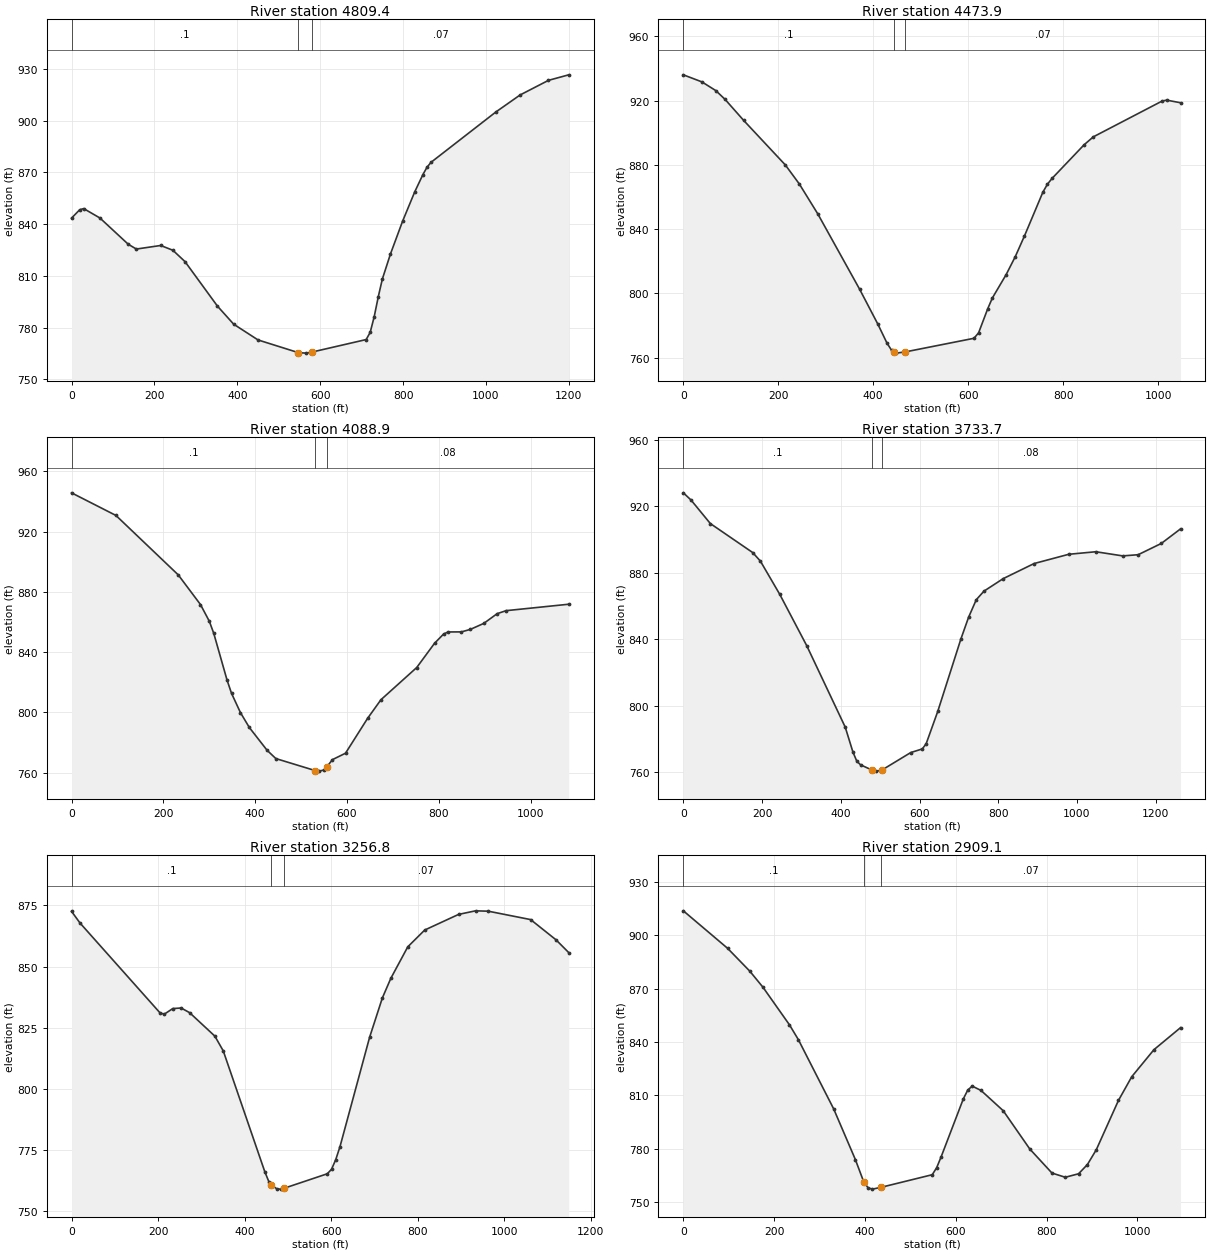
Type RM Length L Ch R = 1 ,4809.4  ,359.7,335.5,311.6
XS GIS Cut Line= 4
     1880108.901      642165.291     1880331.992      642600.621
     1880292.929      642808.954     1880570.273      643223.233
#Sta/Elev= 30
       0  843.45    19.6  848.29    29.4  848.98    68.5  843.54     137  828.29
   156.5  825.54   215.2  827.61   244.6  824.83   273.9  818.24   352.2  792.43
   391.3  781.99     450  772.87     547  765.54     566  765.23     581  765.89
   710.9  773.09   720.7  777.28   730.4  786.41   740.2  797.94     750  808.17
   769.6  822.72   798.9  841.72   828.2  858.72   847.8  868.66   857.5  872.86
   867.3  875.77  1023.7  904.94  1082.4  914.83  1150.8   923.3  1199.7   926.5
#Mann= 3 , 0 , 0
       0      .1       0     547    .045       0     581     .07       0
Bank Sta=547,581
XS Rating Curve= 0 ,0
Exp/Cntr=0.3,0.1

Type RM Length L Ch R = 1 ,4473.9  ,375.6,385,394
XS GIS Cut Line= 4
     1879854.995      642380.786     1880009.943      642718.025
     1880120.971      642824.945     1880373.509      643281.918
#Sta/Elev= 30
       0  936.03    39.1  931.63    68.4  926.21    87.9  920.74     127  907.68
   214.9  879.91   244.2  868.14   283.2  849.48   371.1   802.7   409.7  780.87
   428.9  769.09   438.6  764.58   444.6  763.47   448.2   762.8   467.5  763.56
   612.3  772.04     622  775.47   641.3  790.51     651  797.14     680  811.68
   699.3   822.9   718.6  835.75   757.3  862.94     767  867.96   776.7  871.55
   844.3  892.51   863.7  897.43  1008.7  919.73  1018.4  920.27  1047.4  918.64
#Mann= 3 , 0 , 0
       0      .1       0   444.6    .045       0   467.5     .07       0
Bank Sta=444.6,467.5
XS Rating Curve= 0 ,0
Exp/Cntr=0.3,0.1

Type RM Length L Ch R = 1 ,4088.9  ,348.5,355.1,361.8
XS GIS Cut Line= 4
     1879654.474      642567.852     1879808.554      642964.987
     1879888.849      643147.279     1880153.606      643520.543
#Sta/Elev= 30
       0   945.8    96.8  930.76   232.4   891.3   280.8  871.61   300.1  860.49
   309.8  852.41   338.8   821.3   348.5  812.57   367.9   799.8   387.2  789.93
     426  774.75     445  769.28   530.3  761.33   539.8  760.94   549.3  761.69
   556.4763.9695   568.3  768.58   596.7  772.84   644.6  795.92   673.8  808.35
   751.8  829.77   790.7  845.91   810.2  851.97   819.9  853.38   849.1  853.43
   868.6  855.09   897.8  859.07     927  865.55   946.5  867.53  1082.8   871.8
#Mann= 3 , 0 , 0
       0      .1       0   530.3    .045       0   556.4     .08       0
Bank Sta=530.3,556.4
XS Rating Curve= 0 ,0
Exp/Cntr=0.3,0.1

Type RM Length L Ch R = 1 ,3733.7  ,473.6,477,480.3
XS GIS Cut Line= 2
     1879447.165      642666.677     1879629.457      643916.677
#Sta/Elev= 30
       0  928.22    19.6  923.86    68.6  909.73   176.3  892.27   195.8  887.12
   244.8  867.21   313.4   836.3   411.3  787.26   430.9  772.24   440.7  766.77
   450.4  764.58   479.8   761.4   489.6  760.81  504.05   761.4   577.8  771.99
   607.1  774.17   616.9  777.29   646.3  796.71     705   840.2   724.6  853.32
   744.2  863.92   763.8  869.09   812.8  876.63   891.1  885.68   979.2  891.25
  1047.8  892.78  1116.3  890.28  1155.5  890.99  1214.3  897.77  1263.2  906.54
#Mann= 3 , 0 , 0
       0      .1       0   479.8    .045       0  504.05     .08       0
Bank Sta=479.8,504.05
XS Rating Curve= 0 ,0
Exp/Cntr=0.3,0.1

Type RM Length L Ch R = 1 ,3256.8  ,345.3,347.7,350.1
XS GIS Cut Line= 4
     1879060.724      642747.973     1879055.516      643089.119
      1879058.12      643300.056     1879159.683      643888.598
#Sta/Elev= 30
       0   872.6    19.5  867.85   204.7  831.07   214.5  830.57     234  832.85
   253.4  833.09     273  831.18   331.4  821.58   350.8  815.54   446.7  766.21
   456.2  762.08   461.9  760.77   475.4  759.07     485  759.05  490.64  759.36
   591.3  765.33   601.1  767.17   610.9  771.15   620.7  776.47   689.2  821.19
   718.6  837.22   738.2  845.24   777.3  858.09   816.5  864.96   894.8  871.35
     934  872.81   963.4  872.66  1061.3  869.23    1120  860.96  1149.4  855.74
#Mann= 3 , 0 , 0
       0      .1       0   461.9    .045       0  490.64     .07       0
Bank Sta=461.9,490.64
XS Rating Curve= 0 ,0
Exp/Cntr=0.3,0.1

Type RM Length L Ch R = 1 ,2909.1  ,357.9,355.1,352.4
XS GIS Cut Line= 4
     1878726.523      642757.522     1878742.148      643107.782
     1878722.617      643304.397     1878623.658      643842.157
#Sta/Elev= 30
       0   913.8    97.4  892.71   146.1   879.9   175.3   870.8   233.7  849.63
   253.2  841.33   331.1  802.28   378.8  773.81   397.6     761   407.1  757.84
   416.5  757.14   435.3  758.15   548.2  765.26     558  769.27   567.7   775.3
   616.5  807.89   626.3  812.88   636.1  815.14   655.6  812.68   704.4  801.29
     763  779.72   811.8  766.19   841.1  763.82   870.4  765.78   889.9  770.98
   909.5  779.35   958.3   807.1   987.6  820.45  1036.4  835.64    1095  848.05
#Mann= 3 , 0 , 0
       0      .1       0   397.6    .045       0   435.3     .07       0
Bank Sta=397.6,435.3
XS Rating Curve= 0 ,0
Exp/Cntr=0.3,0.1

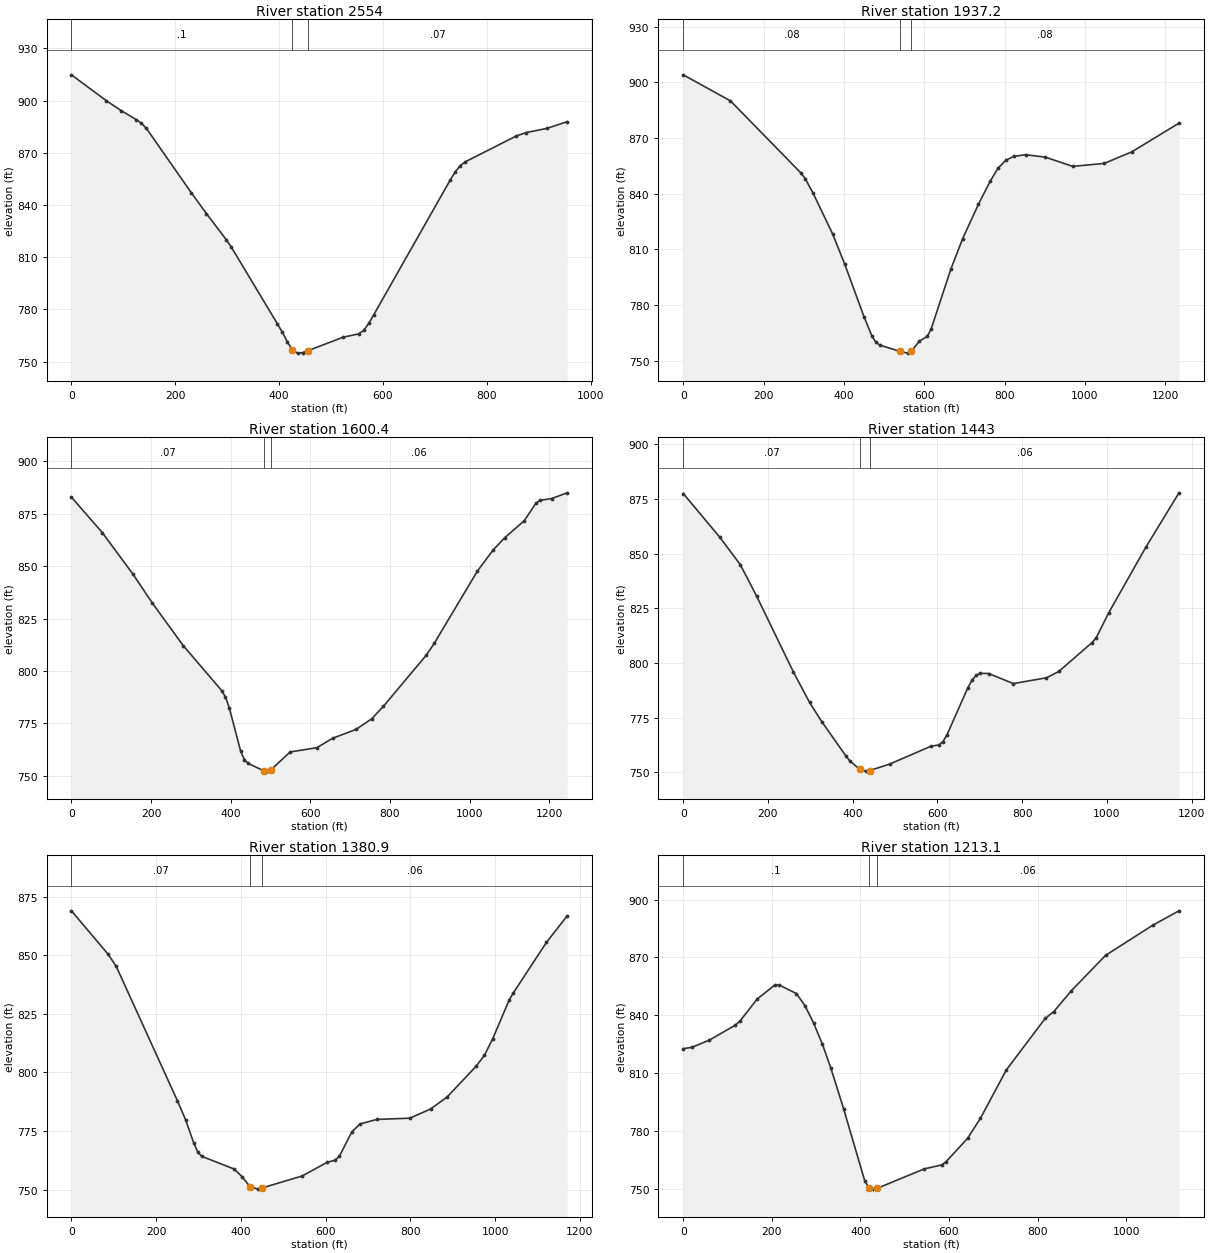
Type RM Length L Ch R = 1 ,2554    ,616.7,616.8,616.9
XS GIS Cut Line= 3
     1878381.905      642738.424     1878379.952      643046.606
     1878387.301      643693.347
#Sta/Elev= 30
       0  914.86    67.4  899.94    96.3   894.2   125.2  889.04   134.8  886.99
   144.5  884.03   231.1  847.02     260  835.12   298.6  819.98   308.2  815.77
   396.4  771.93   406.2  766.97     416  761.38   425.8  756.66   435.6  754.92
   445.4  755.21   455.2  756.28   523.8  764.12   553.2  765.96     563  767.96
   572.8  772.04   582.6  777.07   729.6  854.37   739.4  859.13   749.2  862.73
     759  864.92     857  879.72   876.6   881.7   915.8  884.07     955  887.93
#Mann= 3 , 0 , 0
       0      .1       0   425.8    .045       0   455.2     .07       0
Bank Sta=425.8,455.2
XS Rating Curve= 0 ,0
Exp/Cntr=0.3,0.1

Type RM Length L Ch R = 1 ,1937.2  ,328.8,336.8,344.7
XS GIS Cut Line= 2
     1877770.082      642671.885      1877775.29       643906.26
#Sta/Elev= 30
       0  904.11   117.6  890.05   293.9  850.97   303.7  848.07   323.3  840.29
   372.3  818.11   401.7  802.21   450.6  773.33   470.2  763.01     480  759.81
   489.8  758.28   538.8  755.01   558.4  753.99   568.3  755.05   587.8  760.45
   607.4  762.96   617.2  766.99   666.2  799.23   695.6  815.68   734.8  834.18
   764.1  846.66   783.7  853.73   803.3  858.06   822.9   860.1   852.3  861.02
   901.3  859.72   969.9  854.73  1048.2  856.33  1116.8  862.55  1234.4  878.05
#Mann= 3 , 0 , 0
       0     .08       0   538.8    .045       0   568.3     .08       0
Bank Sta=538.8,568.3
XS Rating Curve= 0 ,0
Exp/Cntr=0.3,0.1

Type RM Length L Ch R = 1 ,1600.4  ,153.8,157.4,160.9
XS GIS Cut Line= 4
     1877547.703      642665.508      1877491.28       643019.24
     1877419.665      643247.105     1877313.328      643886.428
#Sta/Elev= 30
       0  882.95    77.4  866.05   154.9  846.08   203.3  832.35   280.8  812.06
   377.3   790.6   386.9  787.53   396.4  782.36   425.1  761.59   434.6  757.52
   444.2  755.77   482.4  752.34     492  752.12   501.5  752.81   549.3  761.28
   616.7  763.33     656  767.81   714.9  772.05   754.2  777.11   783.6  783.07
   891.6  807.56   911.3  813.14  1019.3  847.54  1058.6  857.58    1088  863.53
  1137.2  871.66  1166.6  880.02  1176.4  881.43  1205.9  882.26  1245.2  885.02
#Mann= 3 , 0 , 0
       0     .07       0   482.4    .045       0   501.5     .06       0
Bank Sta=482.4,501.5
XS Rating Curve= 0 ,0
Exp/Cntr=0.3,0.1

Type RM Length L Ch R = 1 ,1443    ,61.7,62,62.8
XS GIS Cut Line= 4
     1877504.301      642649.449     1877377.131      642971.497
     1877296.835       643131.22     1877155.776       643760.56
#Sta/Elev= 30
       0  877.55    86.6  857.48   134.6  845.03   173.1  830.66   259.7  796.02
   298.2  781.97     327  773.18   383.9  757.51   393.3  755.22   416.7  751.37
   430.9  750.57   440.3  750.85   487.4  753.81   583.6  761.88   603.2  762.57
     613   764.1   622.7  767.31   671.6  788.68   681.4  792.12   691.1  794.36
   700.9  795.31   720.5  795.23   779.1  790.63   857.3  793.27   886.6  796.19
   964.8   809.4   974.5   811.5  1003.8   822.9  1091.8  853.01    1170  877.88
#Mann= 3 , 0 , 0
       0     .07       0   416.7    .045       0   440.3     .06       0
Bank Sta=416.7,440.3
XS Rating Curve= 0 ,0
Exp/Cntr=0.3,0.1

Type RM Length L Ch R = 1 ,1380.9  ,182.7,167.8,152.7
XS GIS Cut Line= 4
     1877445.707      642632.088     1877318.537      642954.136
     1877238.242      643113.858     1877097.183      643743.199
#Sta/Elev= 30
       0  868.94    86.6  850.42   105.8  845.22   250.1  787.93   269.3  779.86
   288.5  770.06   298.2  766.03   307.8  764.22   383.9  758.83   402.7  755.57
   421.5  751.25   440.3  750.25   449.8  750.76   544.6  755.86   603.2  761.67
   622.7  762.61   632.5  764.31   661.8  774.69   681.4  778.05   720.5  779.97
   798.6  780.51   847.5  784.41   886.6  789.54     955  802.64   974.5  807.27
   994.1  814.32  1033.2  830.95  1042.9  833.94  1121.1  855.48    1170   866.8
#Mann= 3 , 0 , 0
       0     .07       0   421.5    .045       0   449.8     .06       0
Bank Sta=421.5,449.8
XS Rating Curve= 0 ,0
Exp/Cntr=0.3,0.1

Type RM Length L Ch R = 1 ,1213.1  ,251.3,257.2,270.9
XS GIS Cut Line= 4
     1877059.422      642651.619     1877109.335      642961.949
     1877131.037       643142.07     1876957.426      643741.029
#Sta/Elev= 30
       0  822.68    19.6  823.38    58.9   827.1   117.9  834.93   127.7  836.89
     167  848.45   206.3  855.62   216.1  855.76   255.4   851.3     275  844.95
   294.7  835.77   314.3  824.97   333.4  812.46   362.1  791.46   409.8  754.07
   419.4   750.5   428.9  749.75   438.4  750.22   544.5  760.28   583.4  762.31
   593.2  763.93   641.9  776.07   671.1  786.56   729.6  811.64   817.3  838.38
   836.8  841.92   875.8  852.61   953.7  871.13  1060.9  886.84  1119.4  894.22
#Mann= 3 , 0 , 0
       0      .1       0   419.4    .045       0   438.4     .06       0
Bank Sta=419.4,438.4
XS Rating Curve= 0 ,0
Exp/Cntr=0.3,0.1

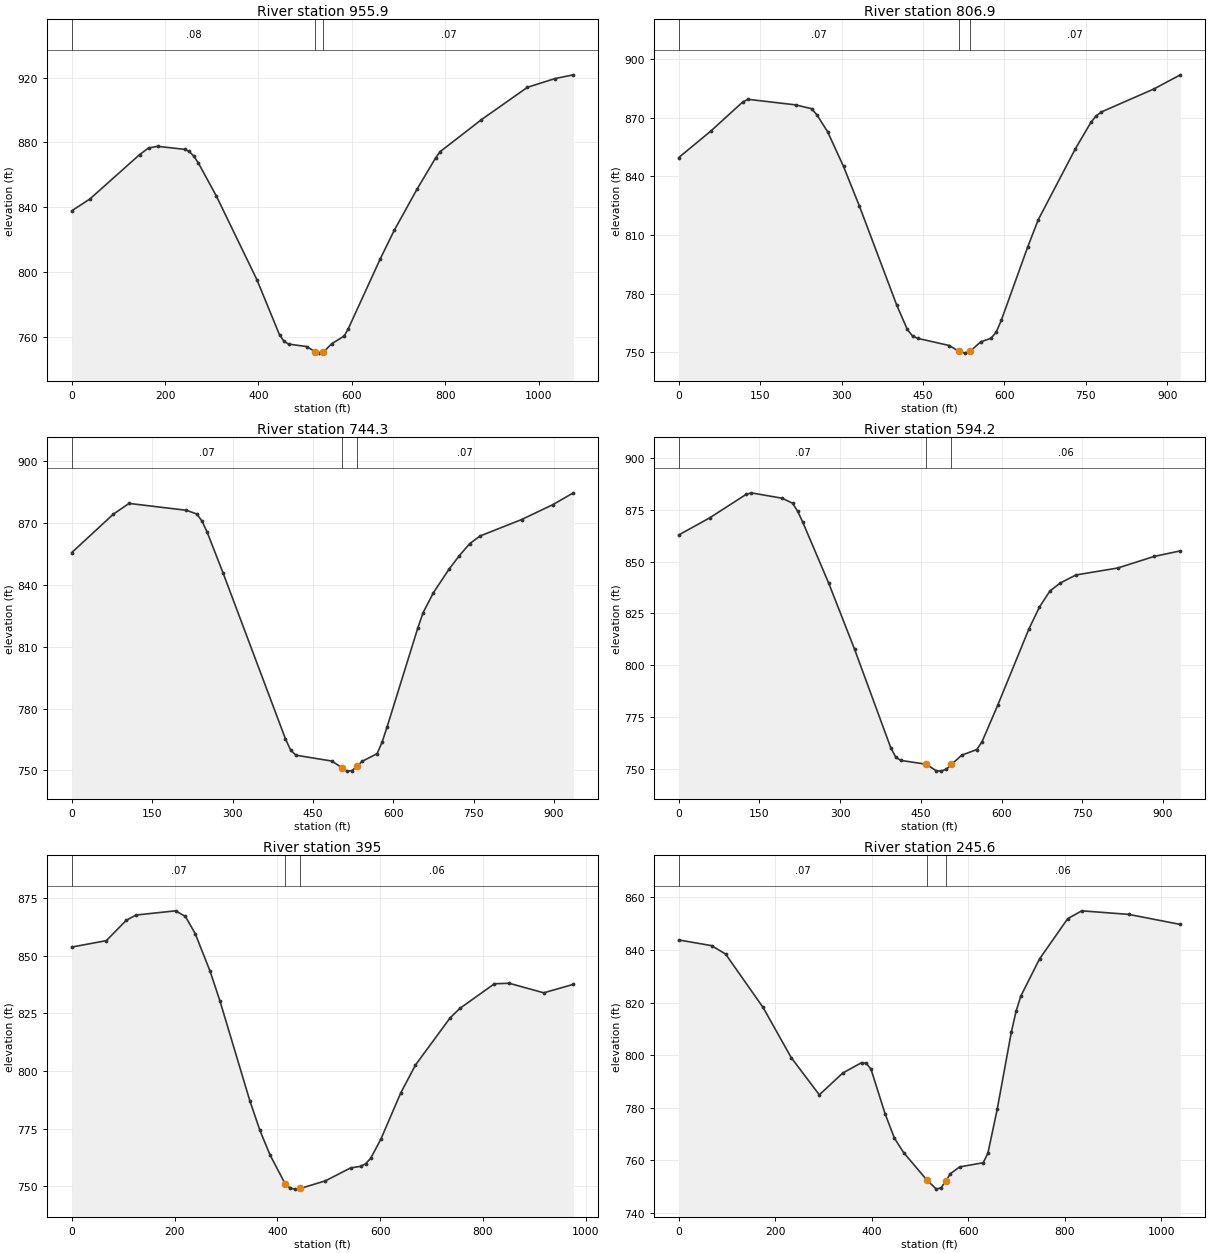
Type RM Length L Ch R = 1 ,955.9   ,137.2,149,160.8
XS GIS Cut Line= 4
     1877016.453      642658.563      1876893.19      643146.411
     1876882.773      643234.952     1876794.231      643708.911
#Sta/Elev= 30
       0  837.79    38.7  845.06   145.2  872.47   164.5   876.6   183.8  877.62
   241.9  875.76   251.6  874.47   261.3  871.61   270.9  867.48   309.6  847.02
   396.7  795.19   445.1  761.15   454.8  757.17   464.5  755.44   503.2  753.93
     521  750.82   529.9  749.86   539.1  750.49   556.7  755.64   583.4  760.39
   592.3  764.89   661.2  808.32   690.7  825.67   739.9   851.3   779.3  870.39
   789.1  874.32   877.7  894.12   976.1   914.1  1035.1  919.48  1074.5   921.8
#Mann= 3 , 0 , 0
       0     .08       0     521    .045       0   539.1     .07       0
Bank Sta=521,539.1
XS Rating Curve= 0 ,0
Exp/Cntr=0.3,0.1

Type RM Length L Ch R = 1 ,806.9   ,64.4,62.7,60.9
XS GIS Cut Line= 4
     1876981.731      642658.563     1876790.759      643066.549
     1876710.898      643186.341     1876578.953      643488.424
#Sta/Elev= 30
       0  849.56    58.8  863.04   117.5  877.88   127.3  879.36   215.4   876.5
   244.8  874.54   254.6   871.4   274.2   862.8   303.6  845.02     333  824.66
   401.5  774.25   421.1   761.7   430.9   758.3   440.7  757.12   498.5  753.48
   515.7  750.59   527.2  749.59   536.8  750.53     556   755.3   575.2  757.19
   584.8  760.27   594.4  766.47   642.9  803.87   662.3  817.76   730.2  853.79
   759.3  867.55     769  870.86   778.6  872.87   875.6  884.67   924.1  891.86
#Mann= 3 , 0 , 0
       0     .07       0   515.7    .045       0   536.8     .07       0
Bank Sta=515.7,536.8
XS Rating Curve= 0 ,0
Exp/Cntr=0.3,0.1

Type RM Length L Ch R = 1 ,744.3   ,149.1,150.1,151
XS GIS Cut Line= 4
     1876948.745      642651.619     1876723.051      643049.188
     1876648.398      643179.397     1876511.245      643478.008
#Sta/Elev= 30
       0  855.78    77.8  874.48     107  879.65     214  876.31   233.4   874.5
   243.2     871   252.9  865.53   282.1  846.05   398.8   765.3   408.5  759.84
   418.3   757.4   485.3  754.56   504.1  751.34   513.4  749.67   522.8  749.93
   532.2     752   541.6   754.4   569.7  758.14   579.1  763.77   588.5  771.24
   645.9  819.35   655.6  826.64   674.9  836.36   703.9  847.69   723.2  854.31
   742.6  860.14   761.9  863.84   839.2  871.81   897.2  878.99   935.9  884.79
#Mann= 3 , 0 , 0
       0     .07       0   504.1    .045       0   532.2     .07       0
Bank Sta=504.1,532.2
XS Rating Curve= 0 ,0
Exp/Cntr=0.3,0.1

Type RM Length L Ch R = 1 ,594.2   ,201.3,199.3,197.2
XS GIS Cut Line= 4
     1876825.481      642594.327     1876624.092      642932.869
     1876539.023      643068.286     1876377.565      643410.299
#Sta/Elev= 30
       0  862.77    57.6  871.03   124.9  882.25   134.5  883.05   192.2  880.45
   211.4  878.09     221  874.17   230.6  868.83   278.6  839.62   326.7  807.81
   393.9  760.45   403.3  755.84   412.7  754.31   459.8  752.46   478.6  749.32
     488  749.15   497.4  750.14   506.8  752.36   525.6  756.81   553.8  759.53
   563.5  763.27   592.6  780.81   650.8  817.65   670.2   828.1   689.6  835.79
     709  839.68   738.1  843.54   815.7  846.88   883.6  852.47     932  855.12
#Mann= 3 , 0 , 0
       0     .07       0   459.8    .045       0   506.8     .06       0
Bank Sta=459.8,506.8
XS Rating Curve= 0 ,0
Exp/Cntr=0.3,0.1

Type RM Length L Ch R = 1 ,395     ,156.6,149.4,142.2
XS GIS Cut Line= 4
     1876750.828      642564.813     1876497.356      642771.411
     1876365.412      643023.147     1876238.676      643365.161
#Sta/Elev= 30
       0  853.78    67.3  856.57   105.8  865.34     125  867.69     202  869.51
   221.2  867.07   240.4  859.54   269.3  843.22   288.5  830.27   346.6     787
   366.2  774.15   385.8  763.54   415.2     751     425   749.1   434.8  748.68
   444.6  748.96   493.6  752.29   542.6  757.88   562.2   758.6     572  759.75
   581.8  762.13   601.4  770.34     640  790.38   668.8  802.57     736  822.97
   755.2  827.16   822.4  837.84   851.2  838.06   918.4  833.92     976  837.58
#Mann= 3 , 0 , 0
       0     .07       0   415.2    .045       0   444.6     .06       0
Bank Sta=415.2,444.6
XS Rating Curve= 0 ,0
Exp/Cntr=0.3,0.1

Type RM Length L Ch R = 1 ,245.6   ,52.2,52.2,52.2
XS GIS Cut Line= 5
     1876697.009      642540.508     1876420.967      642634.258
     1876315.065      642797.452     1876294.231      642901.619
     1876177.912      643333.911
#Sta/Elev= 30
       0  843.82      68  841.66    97.2  838.46   174.9  818.15   233.2   799.1
   291.5  784.94   340.2  793.25   379.1  797.17   388.8   796.9   398.5  794.77
   427.7  777.83   447.2  768.47   466.6  762.92     515  752.44   534.4  749.09
     544  749.65   553.7  752.16   563.3  754.98   582.6  757.55   631.2  759.12
     641  762.73   660.4  779.53   689.6  808.78   699.4  816.67   709.1  822.41
     748  836.59   806.4   851.9   835.6  854.89   932.9  853.54    1040  849.72
#Mann= 3 , 0 , 0
       0     .07       0     515    .045       0   553.7     .06       0
Bank Sta=515,553.7
XS Rating Curve= 0 ,0
Exp/Cntr=0.3,0.1

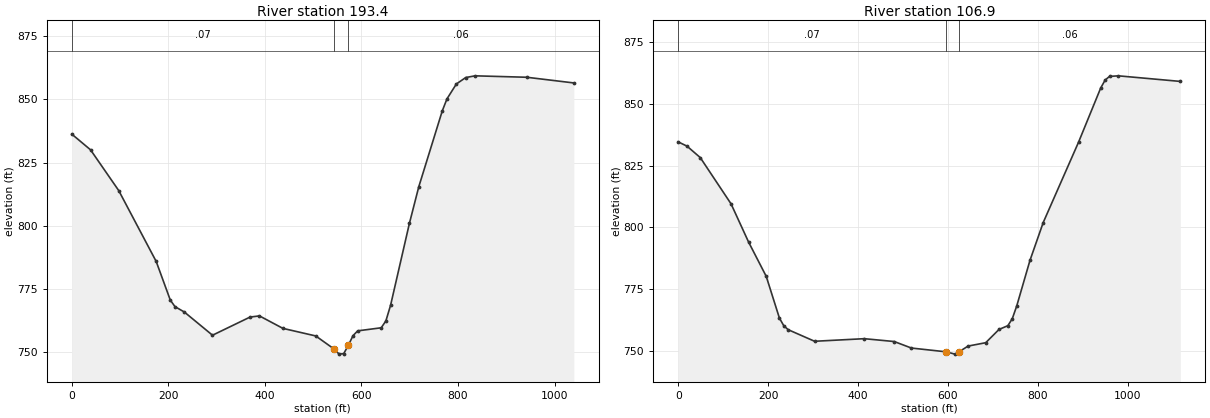
Type RM Length L Ch R = 1 ,193.4   ,77.7,86.5,95.2
XS GIS Cut Line= 5
     1876648.398      642517.938     1876372.356      642611.688
     1876266.453      642774.883      1876245.62      642879.049
     1876129.301      643311.341
#Sta/Elev= 30
       0  836.26    38.9  830.03    97.2  813.91   174.9   785.8   204.1  770.49
   213.8  767.91   233.2  765.77   291.5  756.58   369.4  763.78   388.8  764.23
   437.4  759.29   505.4  756.29     544  751.02   553.7  749.09   563.3  749.28
     573  752.63   582.6  756.42   592.3  758.31     641  759.53   650.7  762.27
   660.4  768.46   699.4  800.91   718.8   815.4   767.5  845.48   777.2  850.23
   796.7  856.13   816.1  858.68   835.6  859.35   942.6  858.78    1040  856.53
#Mann= 3 , 0 , 0
       0     .07       0     544    .045       0     573     .06       0
Bank Sta=544,573
XS Rating Curve= 0 ,0
Exp/Cntr=0.3,0.1

Type RM Length L Ch R = 1 ,106.9   ,107.3,106.9,106.5
XS GIS Cut Line= 6
     1876668.797      642493.199     1876381.037      642589.553
     1876287.894      642678.786     1876195.056      642776.402
     1876149.483      642851.272     1876005.169      643290.725
#Sta/Elev= 30
       0  834.57    19.6  832.83      49  828.22   117.5  809.51   156.6  794.02
   195.8  780.17   225.2  763.26   234.9  760.17   244.7  758.57   303.5  753.88
     414  754.93   480.6  753.78     519  751.14   596.4  749.61   615.9  748.68
   625.6   749.7   645.1  751.94   684.3   753.3   713.9  758.67   733.6  760.19
   743.4     763   753.2  768.09   782.8  786.61   812.3  801.94     891  834.48
   940.2  856.36   950.1  859.59   959.9  861.07   979.6   861.3  1117.4  859.04
#Mann= 3 , 0 , 0
       0     .07       0   596.4    .045       0   625.6     .06       0
Bank Sta=596.4,625.6
XS Rating Curve= 0 ,0
Exp/Cntr=0.3,0.1

Chan Stop Cuts=-1
Use User Specified Reach Order=0
Composite Channel Slope=5